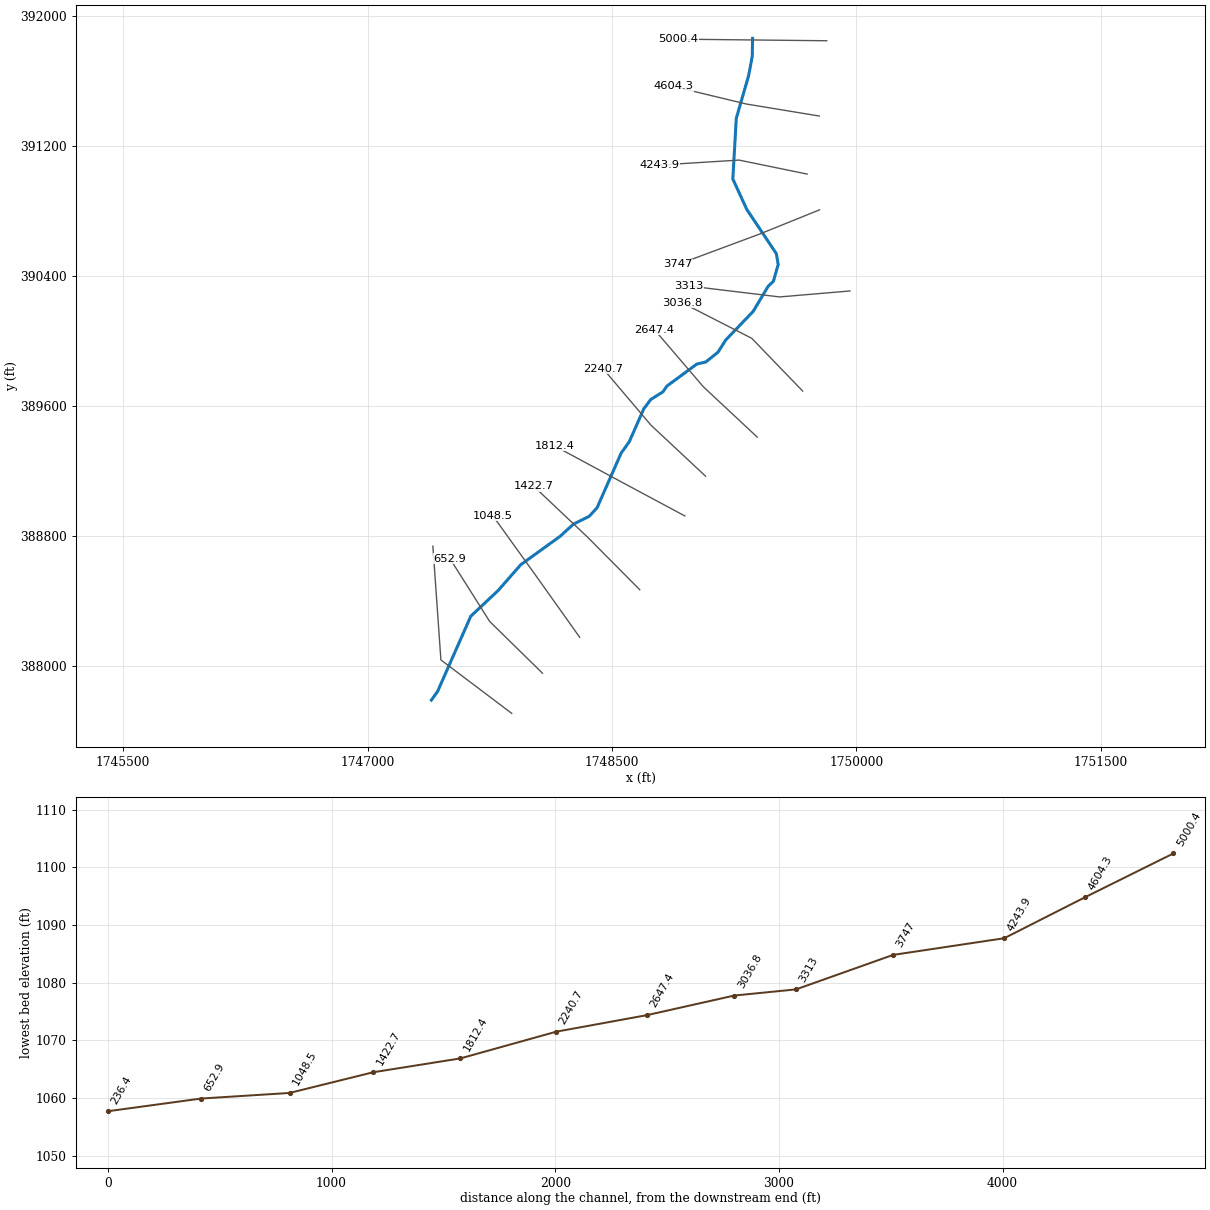
--- NP15.prj (project) ---

Proj Title=NP15
Current Plan=p01
Default Exp/Contr=0,0
English Units
Geom File=g01
Flow File=f01
Plan File=p01
BEGIN DESCRIPTION:
END DESCRIPTION:
DSS Export Rating Curves= 0
DSS Export Rating Curve Sorted= 0
DSS Export Volume Flow Curves= 0
DXF OffsetX= 0
DXF OffsetY= 0
DXF ScaleX= 0
DXF ScaleY= 0

--- NP15.p01 (plan) ---

Plan Title=Floodplain
Program Version=4.00
Geom File=g01
Flow File=f01
K Sum by GR=0
Std Step Tol=0.01
Critical Tol=0.01
Num of Std Step Trials=20
Max Error Tol=0.3
Flow Tol Ratio=0.001
Split Flow NTrial=30
Split Flow Tol=0.02
Split Flow Ratio=0.02
Log Output Level=0
Friction Slope Method=1
Unsteady Friction Slope Method=2
Unsteady Bridges Friction Slope Method=1
Global Log Level=0
CheckData=False
Run HTab=0
Run UNet=0
Run PostProcess=0
UNET Theta=0
UNET Theta Warmup=0
UNET ZTol=0
UNET ZSATol=0
UNET MxIter=0
UNET MaxInSteps=0
UNET DtIC=0
UNET DtMin=0
UNET MaxCRTS=0
UNET WFStab=0
UNET SFStab=0
UNET WFX=0
UNET SFX=0
UNET DSS MLevel=0
UNET DZMax Abort=0
UNET Convert EG Bridges=0
UNET Use Existing IB Tables=0
UNET Froude Limit=0
UNET Froude Power=0
Write IC File=0
Echo Input=False
Echo Output=False
Write Detailed=0

--- NP15.f01 (steady flow) ---

Flow Title=NFF Regression Equation
Program Version=4.00
Number of Profiles=1
Profile Names=P100yr
River Rch & RM=NP15,Main      ,5000.4
346.1000
River Rch & RM=NP15,Main      ,4243.9
373.7098
River Rch & RM=NP15,Main      ,3747
437.3382
River Rch & RM=NP15,Main      ,3313
461.0662
River Rch & RM=NP15,Main      ,3036.8
687.1114
River Rch & RM=NP15,Main      ,2240.7
     722
River Rch & RM=NP15,Main      ,236.4
780.4385
Boundary for River Rch & Prof#=NP15,Main      ,1
Up Type=0
Dn Type=3
Dn Slope=0.005503

--- NP15.g01 (geometry) ---

Geom Title=USGS 3m DEM
Program Version=4.00

River Reach=NP15            ,Main
Reach XY= 30
     1749362.922      391860.647     1749360.718      391749.629
     1749338.524      391631.258     1749262.692       391368.62
     1749241.546      390995.649     1749327.426      390808.204
     1749508.683      390536.319      1749519.78      390469.735
     1749490.188      390366.159     1749458.745      390336.566
     1749366.267      390181.203     1749197.957      390005.495
     1749149.869      389929.663     1749075.886      389870.477
       1749020.4      389857.531     1748837.293      389722.513
     1748813.249      389687.371     1748737.417      389639.283
     1748694.877      389581.946     1748606.098      389380.344
      1748556.16      389310.061     1748408.195      388973.441
     1748360.107      388921.654      1748263.93      388873.565
       1748180.7      388797.733     1747940.257      388623.875
     1747801.891      388465.719     1747633.387      388306.754
     1747429.359      387843.853     1747391.741      387791.319

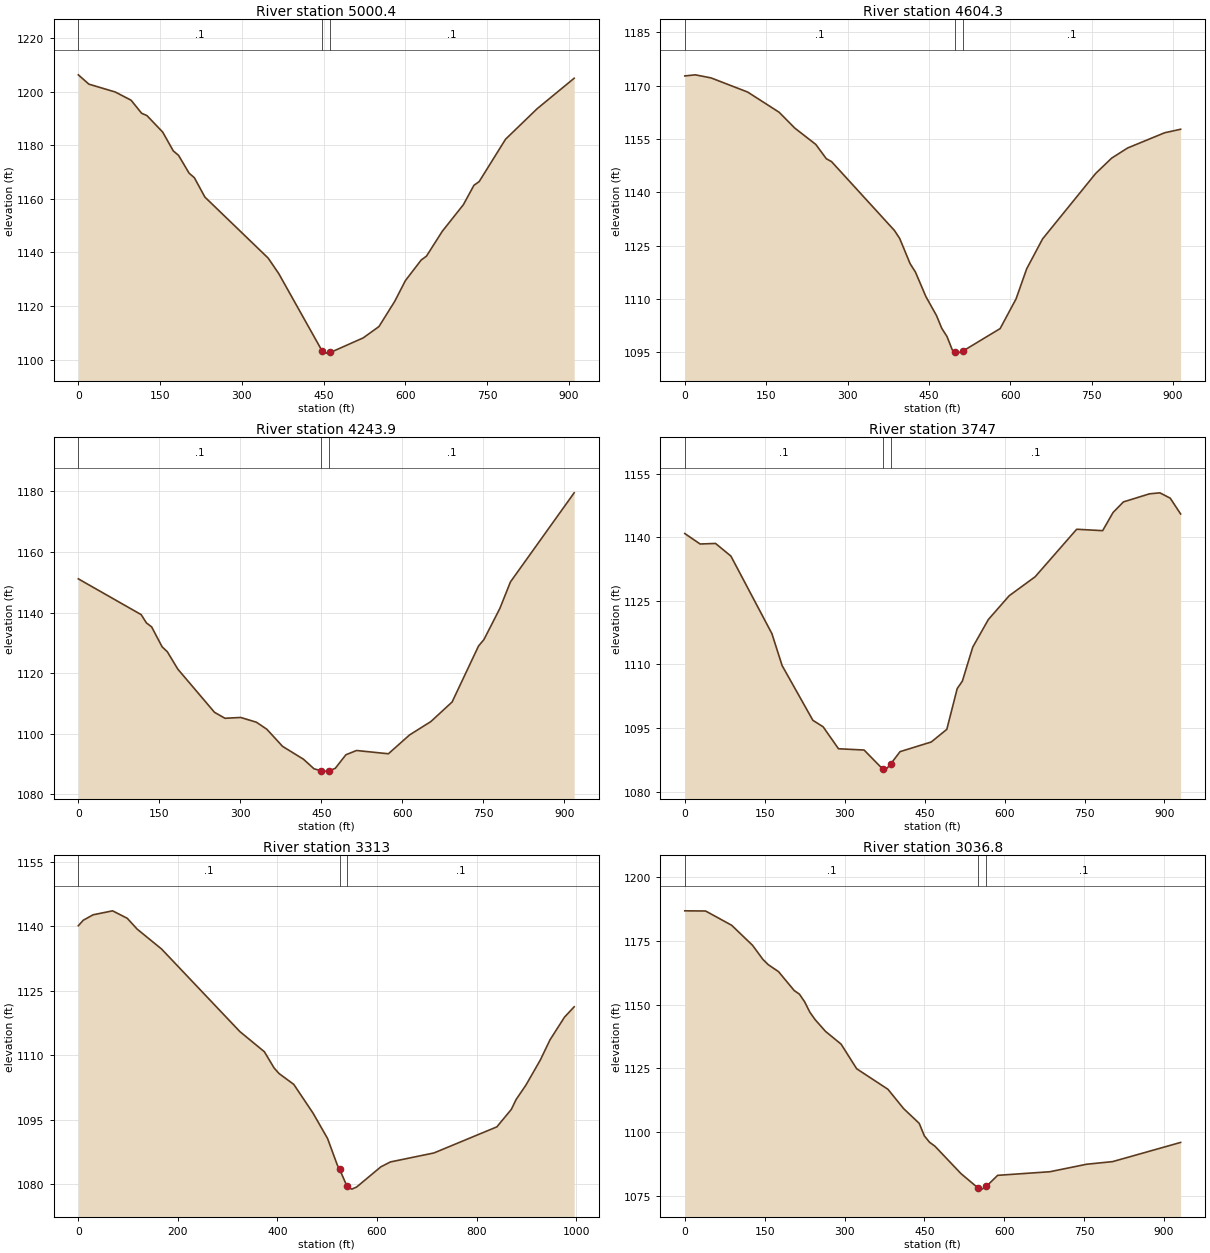
Type RM Length L Ch R = 1 ,5000.4  ,401.218,396.107,390.995
XS GIS Cut Line= 3
     1749817.789      391845.771     1749362.815      391850.648
     1748907.841      391855.524
#Sta/Elev= 30
       0 1206.26    19.4 1202.78    67.8 1199.85    96.8 1196.79   116.2 1191.91
   125.9 1191.06   154.9 1184.88   174.3 1177.87   183.9 1176.23   203.3 1169.57
     213 1167.86   232.3 1160.64   348.5 1137.86   367.9 1132.07   447.5 1103.21
     455 1102.42   462.5 1102.66   522.8  1108.1   551.8 1112.34   580.9 1121.82
   600.2 1129.46   629.3 1137.17   638.9  1138.6     668 1147.89   706.7 1157.81
   726.1 1165.05   735.7 1166.43   784.1 1182.24   842.2 1193.64     910 1204.98
#Mann= 3 , 0 , 0
       0      .1       0   447.5    .045       0   462.5      .1       0
Bank Sta=447.5,462.5
XS Rating Curve= 0 ,0
Exp/Cntr=0.3,0.1

Type RM Length L Ch R = 1 ,4604.3  ,353.602,360.464,367.326
XS GIS Cut Line= 3
     1749772.292      391382.824     1749324.282      391456.791
     1748877.297      391564.518
#Sta/Elev= 30
       0 1172.76    19.3 1173.07    48.3 1172.21   115.9 1168.22   173.9 1162.54
   202.9 1158.07   241.5 1153.49   260.9 1149.47   270.5 1148.66   386.4  1129.3
   396.1 1127.04   415.4 1119.93   425.1 1117.61   444.4  1110.7   463.9 1105.38
   473.6 1101.79   483.4 1099.44   493.2 1095.65   498.4  1095.2     503  1094.8
   512.8  1095.4   581.2  1101.7   610.6 1110.06   630.2 1118.53   659.5 1126.93
   757.3 1145.33   786.7 1149.63     816 1152.48   884.5 1156.78   913.9 1157.76
#Mann= 3 , 0 , 0
       0      .1       0   498.4    .045       0   512.8      .1       0
Bank Sta=498.4,512.8
XS Rating Curve= 0 ,0
Exp/Cntr=0.3,0.1

Type RM Length L Ch R = 1 ,4243.9  ,489.34,496.818,504.052
XS GIS Cut Line= 3
     1749697.854      391025.884      1749279.82      391111.928
      1748789.12      391081.544
#Sta/Elev= 30
       0 1151.17   116.4 1139.36   126.1 1136.63   135.8 1135.31   155.2 1128.74
   164.9  1127.1   184.3 1121.37   252.2 1107.13   271.6 1105.15   300.7 1105.42
   329.8 1103.86   349.2 1101.53   378.3 1095.88   417.1 1091.63   436.6 1088.47
   449.3 1087.87   456.3 1087.71   464.3 1087.76     476 1088.65   495.6 1093.11
   515.3 1094.52   574.3 1093.44   613.6 1099.66     653 1104.07   692.3 1110.52
   741.4 1129.04   751.3 1131.13   780.8 1141.41   800.4 1150.16   918.4 1179.56
#Mann= 3 , 0 , 0
       0      .1       0   449.3    .045       0   464.3      .1       0
Bank Sta=449.3,464.3
XS Rating Curve= 0 ,0
Exp/Cntr=0.3,0.1

Type RM Length L Ch R = 1 ,3747    ,445.711,434.019,422.571
XS GIS Cut Line= 3
     1749773.391      390805.915     1749408.149      390657.844
     1748905.757      390470.633
#Sta/Elev= 30
       0 1140.91    28.8 1138.44    57.7 1138.57    86.5 1135.59   163.4 1117.29
   182.6 1109.74   240.3 1096.82   259.5 1095.29   288.4  1090.1   336.4  1089.8
   371.6 1085.28   374.9 1084.82   386.6 1086.57   403.9 1089.42   462.4  1091.7
   491.6 1094.68   511.1  1104.3   520.8 1106.08   540.3  1114.1   569.6 1120.62
   608.6 1126.22   657.3  1130.7   735.3 1141.92     784 1141.59   803.5 1145.87
     823 1148.38   871.8 1150.28   891.3 1150.52   910.8 1149.26   930.3 1145.53
#Mann= 3 , 0 , 0
       0      .1       0   371.6    .045       0   386.6      .1       0
Bank Sta=371.6,386.6
XS Rating Curve= 0 ,0
Exp/Cntr=0.3,0.1

Type RM Length L Ch R = 1 ,3313    ,284.228,276.205,268.182
XS GIS Cut Line= 3
     1749960.176      390307.127     1749529.073      390270.391
     1748969.867      390338.007
#Sta/Elev= 30
       0 1140.15     9.8 1141.42    29.5 1142.69    68.8 1143.62    98.3 1141.88
     118 1139.38   167.2 1134.73   324.5 1115.51   373.7 1110.82   393.3 1107.03
   403.2 1105.74   432.7 1103.23   471.5 1096.52   500.6 1090.63   520.1 1084.48
   524.8 1083.47   539.8 1079.46   549.2 1078.84   558.9 1079.32   607.5 1084.02
   626.9 1085.17   714.3 1087.26   840.6 1093.33   869.7  1097.4   879.4 1099.72
   898.8 1103.01     928 1108.91   947.4 1113.59   976.5 1118.87   995.9 1121.28
#Mann= 3 , 0 , 0
       0      .1       0   524.8    .045       0   539.8      .1       0
Bank Sta=524.8,539.8
XS Rating Curve= 0 ,0
Exp/Cntr=0.3,0.1

Type RM Length L Ch R = 1 ,3036.8  ,398.482,389.434,380.386
XS GIS Cut Line= 3
     1749669.993      389691.785     1749357.712      390015.971
     1748929.339      390235.152
#Sta/Elev= 30
       0 1186.65    39.1 1186.58    88.1 1180.99   127.2 1173.17   146.8 1167.63
   156.6 1165.61   176.1 1162.85   205.5 1155.47   215.3 1154.05   225.1 1151.06
   234.8 1147.03   244.6 1144.13   264.2 1139.51   293.6 1134.49   322.9 1124.85
   381.6 1116.83     411 1109.27   440.3 1103.51   450.1 1098.56   459.9 1096.07
   469.8 1094.58   518.9 1083.81   551.3 1078.14   558.2 1077.77   566.3 1078.83
   587.6 1083.16   685.8 1084.58   754.6  1087.5   803.7 1088.54   931.3 1096.04
#Mann= 3 , 0 , 0
       0      .1       0   551.3    .045       0   566.3      .1       0
Bank Sta=551.3,566.3
XS Rating Curve= 0 ,0
Exp/Cntr=0.3,0.1

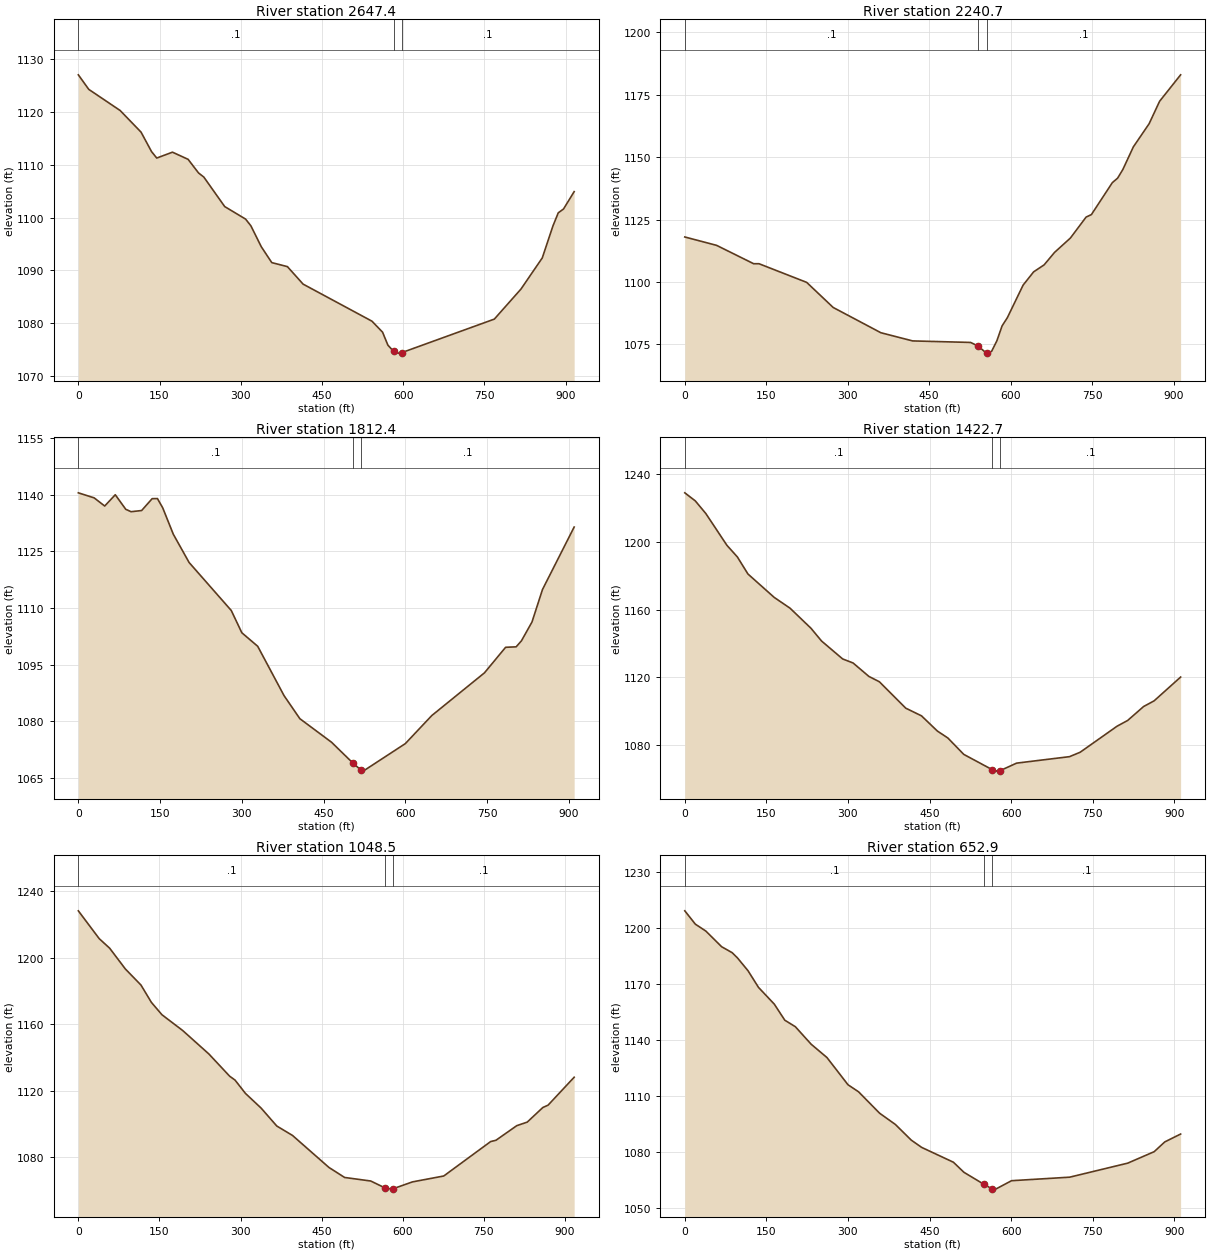
Type RM Length L Ch R = 1 ,2647.4  ,408.006,406.731,405.457
XS GIS Cut Line= 3
     1749391.122      389408.476     1749059.967      389718.636
     1748759.964      390069.881
#Sta/Elev= 30
       0 1126.98    19.3 1124.23    77.2 1120.24   115.8 1116.15   135.2 1112.47
   144.8 1111.25   173.8 1112.36   202.7 1111.01     222 1108.43   231.7 1107.66
   270.3 1102.08   308.9 1099.71   318.6 1098.45   337.9 1094.48   357.2 1091.49
   386.1 1090.73   415.1 1087.42   542.2 1080.42   561.8 1078.34   571.7 1075.88
   582.4  1074.7   591.3 1074.38   597.4 1074.48   768.2 1080.81   817.4 1086.49
   856.7 1092.37   876.3 1098.38   886.2 1100.89     896 1101.63   915.6  1104.9
#Mann= 3 , 0 , 0
       0      .1       0   582.4    .045       0   597.4      .1       0
Bank Sta=582.4,597.4
XS Rating Curve= 0 ,0
Exp/Cntr=0.3,0.1

Type RM Length L Ch R = 1 ,2240.7  ,419.083,428.299,437.516
XS GIS Cut Line= 3
     1749074.015      389168.287     1748739.314      389481.703
     1748445.771      389828.532
#Sta/Elev= 30
       0 1118.02    58.5 1114.67   126.8 1107.31   136.6 1107.31   224.4 1099.84
   273.2 1089.79     361 1079.67   419.5 1076.39   526.2 1075.78   540.5 1074.28
   555.2  1071.5   555.5 1071.52   564.9 1072.21   574.5 1076.39   584.2 1082.41
   593.9  1085.7   622.9 1098.74   642.2 1104.04   661.6 1106.86   680.9 1111.87
   709.9 1117.58   738.9    1126   748.6 1126.98   787.2 1139.79   796.9 1141.58
   806.6 1145.08   825.9 1154.12   854.9 1163.38   874.2 1172.38   912.9 1182.97
#Mann= 3 , 0 , 0
       0      .1       0   540.5    .045       0   555.5      .1       0
Bank Sta=540.5,555.5
XS Rating Curve= 0 ,0
Exp/Cntr=0.3,0.1

Type RM Length L Ch R = 1 ,1812.4  ,395.348,389.607,383.63
XS GIS Cut Line= 3
     1748946.958      388923.688     1748546.102      389138.957
     1748145.772      389355.199
#Sta/Elev= 30
       0 1140.45      29 1139.12    48.4 1136.96    67.8 1139.94    87.1 1136.09
    96.8 1135.46   116.2 1135.77   135.5 1138.91   145.2 1138.93   154.9 1136.48
   174.3 1129.51   203.3 1122.03   280.7 1109.34   300.1 1103.45   329.2 1099.88
   377.6 1086.82   406.6 1080.73   464.7 1074.51   504.6 1068.91   519.6 1067.05
   522.8 1066.87   600.2 1074.15   648.6 1081.55   745.4 1092.86   784.2 1099.61
   803.5 1099.73   813.2 1101.31   832.6 1106.29   851.9 1114.89     910  1131.4
#Mann= 3 , 0 , 0
       0      .1       0   504.6    .045       0   519.6      .1       0
Bank Sta=504.6,519.6
XS Rating Curve= 0 ,0
Exp/Cntr=0.3,0.1

Type RM Length L Ch R = 1 ,1422.7  ,378.874,374.279,369.92
XS GIS Cut Line= 3
     1748670.316       388469.88     1748350.428      388792.921
     1748018.501      389107.227
#Sta/Elev= 30
       0 1229.09    19.3 1224.32    38.7 1216.83    77.4 1198.08    96.7 1191.16
   116.1 1181.08   164.4 1167.24   193.5 1160.86   232.1 1148.96   251.5 1141.43
   290.2 1130.85   309.5 1128.43   338.6 1120.48   357.9 1117.32   406.3 1101.72
   435.3 1097.17   464.4  1088.2   483.8 1084.06     513 1074.38     565 1065.39
   571.3 1064.47     580 1064.78   610.2  1069.2   707.5 1073.03     727 1075.63
     795 1091.06   814.5 1094.46   843.7 1102.67   863.1 1106.06   911.8 1120.11
#Mann= 3 , 0 , 0
       0      .1       0     565    .045       0     580      .1       0
Bank Sta=565,580
XS Rating Curve= 0 ,0
Exp/Cntr=0.3,0.1

Type RM Length L Ch R = 1 ,1048.5  ,396.934,395.581,394.227
XS GIS Cut Line= 3
     1748301.775      388177.491     1748033.467      388555.655
     1747769.359      388924.217
#Sta/Elev= 30
       0 1228.28    38.6 1211.56      58 1205.78    86.9 1193.34   115.9 1183.62
   135.2 1173.19   154.6 1165.79   193.2 1156.24   241.5 1142.16   280.1 1128.74
   289.8 1126.49   309.1 1118.46   338.1 1109.62   367.1 1098.84   396.1 1093.18
   463.7 1073.88   492.6 1067.89   540.9 1065.76   566.4 1061.74   579.4 1060.88
   581.4 1061.02     618 1065.23   675.9 1068.78   762.7  1089.5   772.4 1090.26
     811 1099.06   830.3 1101.19   859.2 1109.98   868.9  1111.4   917.1 1128.18
#Mann= 3 , 0 , 0
       0      .1       0   566.4    .045       0   581.4      .1       0
Bank Sta=566.4,581.4
XS Rating Curve= 0 ,0
Exp/Cntr=0.3,0.1

Type RM Length L Ch R = 1 ,652.9   ,408.205,416.438,424.671
XS GIS Cut Line= 3
     1748073.497      387956.491     1747748.934      388275.369
     1747505.361      388661.717
#Sta/Elev= 30
       0 1208.95    19.4 1201.81    38.7 1198.11    67.8 1189.71    87.1 1186.54
    96.8 1183.75   116.2 1176.89   135.5 1167.96   164.6 1158.97   183.9 1150.37
   203.3 1146.89   232.3 1137.53   261.4 1130.38   300.1  1115.8   319.5 1112.04
   358.2 1100.57   387.2 1094.54   416.3 1086.18   435.6 1082.25   493.9 1074.32
   513.3 1068.91   550.4 1062.43   565.4 1059.97   571.6 1059.91   600.8 1064.42
   707.7 1066.31   814.5 1073.83   863.1 1079.97   882.6  1085.2   911.7 1089.41
#Mann= 3 , 0 , 0
       0      .1       0   550.4    .045       0   565.4      .1       0
Bank Sta=550.4,565.4
XS Rating Curve= 0 ,0
Exp/Cntr=0.3,0.1

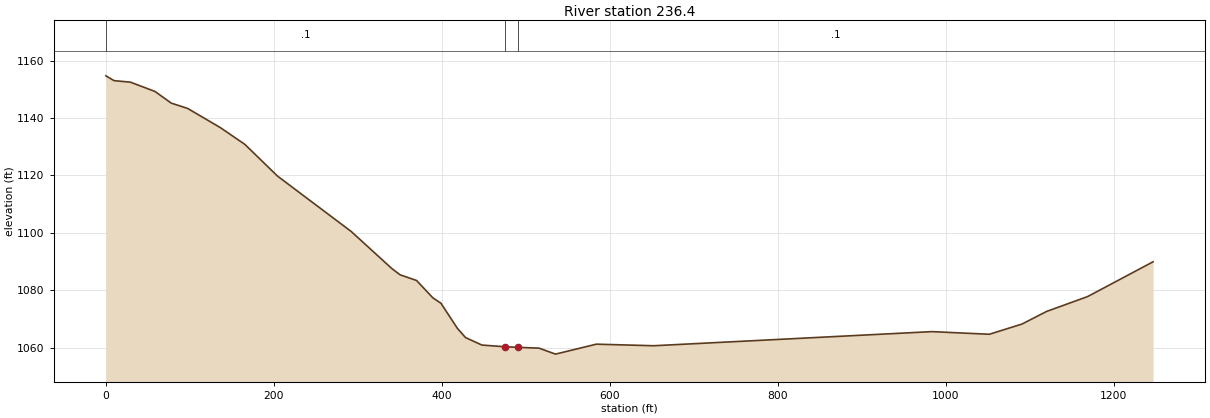
Type RM Length L Ch R = 1 ,236.4   ,234.129,236.45,238.77
XS GIS Cut Line= 3
     1747884.764      387709.527     1747450.101      388038.136
     1747400.838      388738.083
#Sta/Elev= 30
       0 1154.69     9.7 1153.01    29.2 1152.48    58.4 1149.25    77.8 1145.18
    97.3 1143.33   136.2 1136.65   165.4 1130.81   204.3 1119.75   291.9 1100.48
   340.6 1087.48   350.3 1085.34   369.8 1083.38   389.2 1077.34   398.9 1075.43
   418.4 1066.71   428.1 1063.49   447.6 1060.87     475 1060.28     490 1060.08
   515.7 1059.79   535.2 1057.71   583.9 1061.18   652.1 1060.63   983.4 1065.55
  1051.7 1064.63  1090.6 1068.19  1119.9 1072.59  1168.6 1077.75  1246.6 1089.88
#Mann= 3 , 0 , 0
       0      .1       0     475    .045       0     490      .1       0
Bank Sta=475,490
XS Rating Curve= 0 ,0
Exp/Cntr=0.3,0.1

Chan Stop Cuts=-1
Use User Specified Reach Order=0